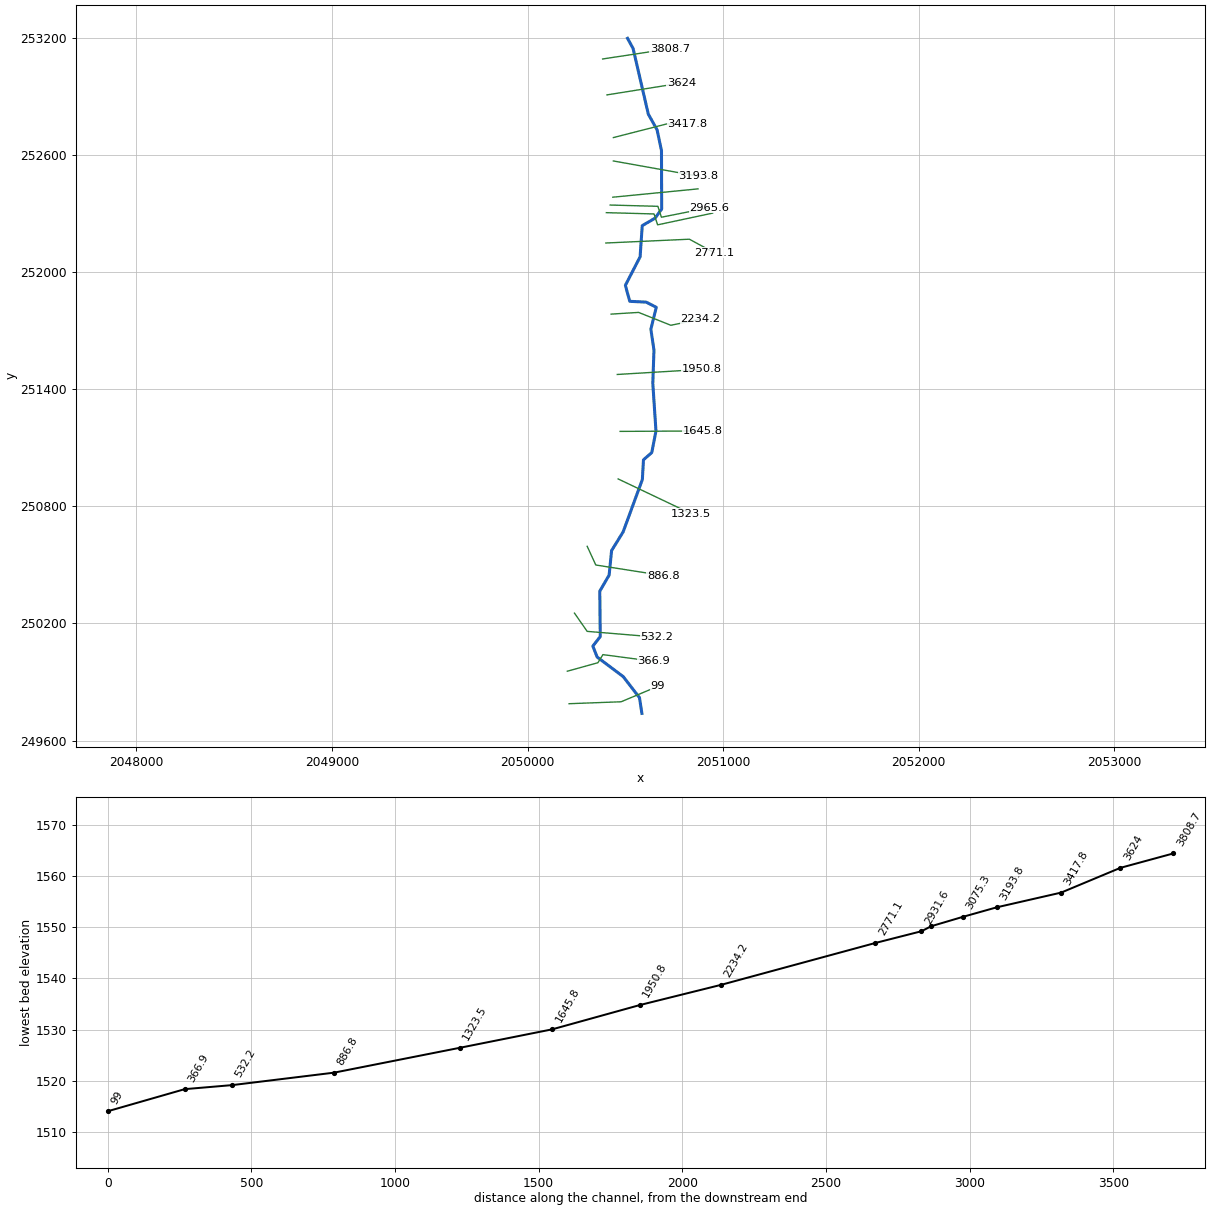
--- BUGGYBR.prj (project) ---

Proj Title=BUGGYBR
Current Plan=p01
Geom File=g01
Flow File=f01
Plan File=p01
DSS Export Rating Curves=0
DSS Export Rating Curve Sorted=0
DSS Export Volume Flow Curves=0
DXF OffsetX=0
DXF OffsetY=0
DXF ScaleX=0
DXF ScaleY=0

--- BUGGYBR.p01 (plan) ---

Plan Title=Floodplain
Program Version=4.00
Geom File=g01
Flow File=f01
K Sum by GR=0
Std Step Tol=0.01
Critical Tol=0.01
Num of Std Step Trials=20
Max Error Tol=0.3
Flow Tol Ratio=0.001
Split Flow NTrial=30
Split Flow Tol=0.02
Split Flow Ratio=0.02
Log Output Level=0
Friction Slope Method=1
Unsteady Friction Slope Method=2
Unsteady Bridges Friction Slope Method=1
Global Log Level=0
CheckData=False
Run HTab=0
Run UNet=0
Run PostProcess=0
UNET Theta=0
UNET Theta Warmup=0
UNET ZTol=0
UNET ZSATol=0
UNET MxIter=0
UNET MaxInSteps=0
UNET DtIC=0
UNET DtMin=0
UNET MaxCRTS=0
UNET WFStab=0
UNET SFStab=0
UNET WFX=0
UNET SFX=0
UNET DSS MLevel=0
UNET DZMax Abort=0
UNET Convert EG Bridges=0
UNET Use Existing IB Tables=0
UNET Froude Limit=0
UNET Froude Power=0
Write IC File=0
Echo Input=False
Echo Output=False
Write Detailed=0

--- BUGGYBR.f01 (steady flow) ---

Flow Title=2010 USGS WV Regression Equation
Program Version=4.00
Number of Profiles=1
Profile Names=P100yr
River Rch & RM=BUGGYBR,Main      ,3808.7
549.8012
River Rch & RM=BUGGYBR,Main      ,3417.8
583.4379
River Rch & RM=BUGGYBR,Main      ,99
636.1600
Boundary for River Rch & Prof#=BUGGYBR,Main      ,1
Up Type=0
Dn Type=3
Dn Slope=0.008796

--- BUGGYBR.g01 (geometry) ---

Geom Title=LiDAR
Program Version=4.00

River Reach=BUGGYBR     ,Main
Reach XY= 30
     2050510.944      253198.033     2050539.443      253145.949
     2050617.137      252809.684     2050662.057      252729.185
     2050684.551      252622.552     2050685.554      252323.386
     2050651.922      252276.707     2050586.143      252238.148
     2050575.234      252078.577     2050499.849      251932.338
     2050522.359      251850.470     2050606.214      251846.345
     2050657.906      251820.073     2050630.307      251707.437
     2050646.115      251600.238     2050640.181      251430.447
     2050656.349      251186.082     2050634.995      251075.666
     2050592.469      251038.433     2050586.740      250937.391
     2050488.303      250668.641     2050429.449      250573.329
     2050416.765      250447.280     2050369.032      250365.516
     2050371.453      250132.697     2050333.644      250083.840
     2050355.515      250027.734     2050488.823      249927.495
     2050572.009      249819.645     2050584.376      249739.111

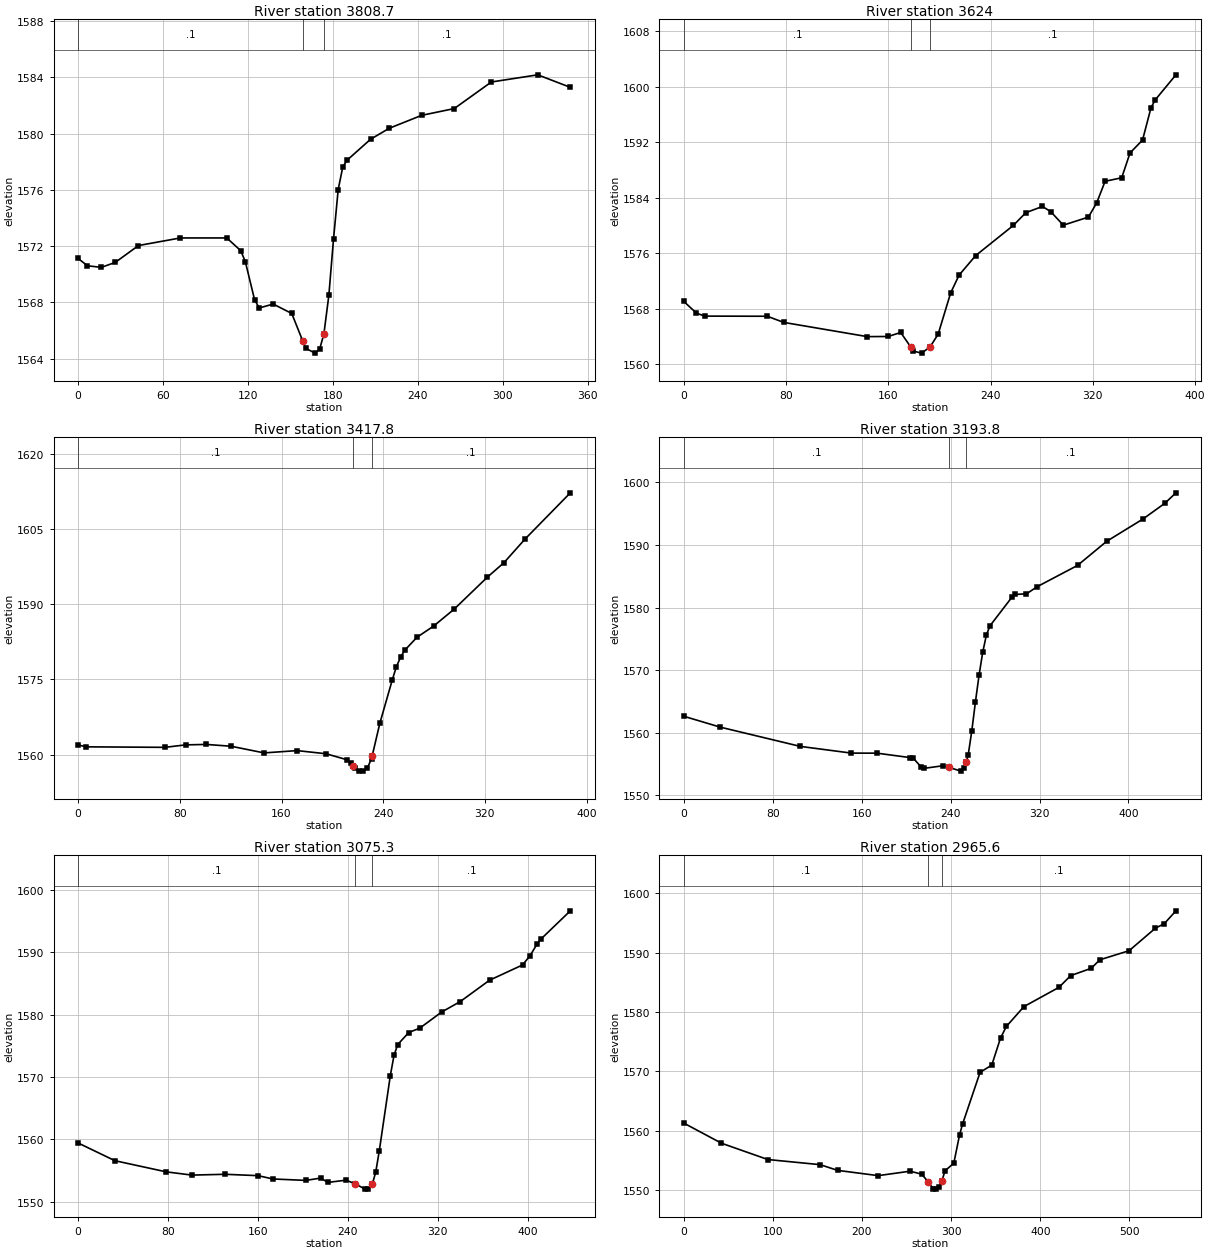
Type RM Length L Ch R = 1 ,3808.7,184.4,184.8,184.8
XS GIS Cut Line= 2
     2050383.553      253092.294     2050727.303      253144.378
#Sta/Elev= 30
       0 1571.12     6.6 1570.60    16.4 1570.49    26.2 1570.84    42.6 1572.04
    72.2 1572.58   105.0 1572.58   114.8 1571.68   118.1 1570.90   124.6  1568.2
   127.9 1567.60   137.8 1567.88   150.9 1567.21   158.6 1565.27   160.7 1564.74
   167.3 1564.39   170.6 1564.67   173.6 1565.75   177.1 1568.49   180.4 1572.50
   183.7 1576.02   187.0 1577.65   190.2 1578.13   206.6 1579.60   219.8 1580.38
   242.7 1581.30   265.7 1581.78   291.9 1583.67   324.7 1584.18   347.7 1583.29
#Mann= 3 , 0 , 0
       0     0.1       0   158.6   0.045       0   173.6     0.1       0
Bank Sta=158.6,173.6
Exp/Cntr=0.3,0.1

Type RM Length L Ch R = 1 ,3624,204.1,206.2,208.4
XS GIS Cut Line= 2
     2050406.123      252908.266     2050786.331      252969.030
#Sta/Elev= 30
       0 1569.04     9.8 1567.36    16.3 1566.91    65.3 1566.89    78.3 1566.00
   143.6 1563.95   159.9 1563.97   169.7 1564.55   177.6 1562.45   179.5 1561.87
   186.0 1561.57   192.6 1562.44   199.0 1564.30   208.8 1570.26   215.4 1572.83
   228.4 1575.65   257.8 1579.99   267.6 1581.83   280.6 1582.73   287.1 1581.98
   296.9 1580.03   316.5 1581.19   323.0 1583.23   329.6 1586.36   342.6 1586.87
   349.1 1590.45   358.9 1592.31   365.5 1596.96   368.7 1598.08   385.0 1601.72
#Mann= 3 , 0 , 0
       0     0.1       0   177.6   0.045       0   192.6     0.1       0
Bank Sta=177.6,192.6
Exp/Cntr=0.3,0.1

Type RM Length L Ch R = 1 ,3417.8,233.4,224,214
XS GIS Cut Line= 3
     2050438.588      252689.473     2050709.421      252758.918
     2050817.060      252757.181
#Sta/Elev= 30
       0 1561.95     6.5 1561.58    68.3 1561.48    84.5 1561.97   100.8 1562.06
   120.3 1561.70   146.3 1560.37   172.3 1560.83   195.1 1560.20   211.3 1559.02
   214.6 1558.42   216.3 1557.81   217.8 1557.27   221.1 1556.74   224.3 1556.83
   227.6 1557.40   230.8 1559.22   231.3 1559.75   237.3 1566.24   247.1 1574.89
   250.3 1577.51   253.6 1579.42   256.8 1580.79   266.6 1583.43   279.6 1585.63
   295.9 1589.04   322.0 1595.41   335.0 1598.28   351.4 1602.94   387.2 1612.20
#Mann= 3 , 0 , 0
       0     0.1       0   216.3   0.045       0   231.3     0.1       0
Bank Sta=216.3,231.3
Exp/Cntr=0.3,0.1

Type RM Length L Ch R = 1 ,3193.8,112,118.5,124.5
XS GIS Cut Line= 2
     2050438.588      252569.681     2050874.352      252491.556
#Sta/Elev= 30
       0 1562.64    32.8 1560.90   104.9 1557.82   150.8 1556.75   173.8 1556.74
   203.3 1556.04   206.6 1555.91   213.2 1554.60   216.4 1554.32   232.8 1554.72
     239 1554.45   249.2 1553.87   252.5 1554.41     254 1555.31   255.8 1556.38
   259.1 1560.29   262.4 1564.98   265.6 1569.16   268.9 1572.84   272.2 1575.61
   275.5 1577.10   295.1 1581.64   298.4 1582.11   308.3 1582.20   318.1 1583.36
   354.2 1586.74   380.4 1590.59   413.2 1594.17   432.9 1596.69   442.7 1598.34
#Mann= 3 , 0 , 0
       0     0.1       0     239   0.045       0     254     0.1       0
Bank Sta=239,254
Exp/Cntr=0.3,0.1

Type RM Length L Ch R = 1 ,3075.3,133.2,109.7,69.6
XS GIS Cut Line= 2
     2050435.637      252383.961     2050871.577      252426.633
#Sta/Elev= 30
       0 1559.40    32.7 1556.56    78.4 1554.77   101.3 1554.25   130.8 1554.38
   160.2 1554.16   173.2 1553.63   202.7 1553.40   215.7 1553.77   222.3 1553.08
   238.6 1553.44   246.8 1552.82   255.0 1552.04   258.2 1552.00   261.8 1552.83
   264.8 1554.70   268.0 1558.15   277.8 1570.20   281.1 1573.46   284.4 1575.19
   294.2 1577.12   304.0 1577.82   323.6 1580.42   340.0 1582.08   366.1 1585.51
   395.5 1587.96   402.1 1589.43   408.6 1591.37   411.9 1592.12   438.0 1596.64
#Mann= 3 , 0 , 0
       0     0.1       0   246.8   0.045       0   261.8     0.1       0
Bank Sta=246.8,261.8
Exp/Cntr=0.3,0.1

Type RM Length L Ch R = 1 ,2965.6,41.1,34,47.1
XS GIS Cut Line= 4
     2050422.002      252343.832     2050666.139      252337.274
     2050684.286      252281.413     2050928.692      252330.141
#Sta/Elev= 30
       0 1561.30    42.3 1557.91    94.4 1555.16   153.0 1554.30   172.6 1553.34
   218.2 1552.45   254.0 1553.20   267.1 1552.69   274.6 1551.33   280.1 1550.22
   283.4 1550.18   286.6 1550.53   289.6 1551.56   293.2 1553.27   303.0 1554.55
   309.5 1559.33   312.8 1561.12   332.5 1569.85   345.6 1571.05   355.4 1575.61
   362.0 1577.57   381.7 1580.91   421.0 1584.15   434.1 1586.12   457.1 1587.35
   466.9 1588.79   499.7 1590.32   529.2 1594.11   539.1 1594.86   552.2 1597.03
#Mann= 3 , 0 , 0
       0     0.1       0   274.6   0.045       0   289.6     0.1       0
Bank Sta=274.6,289.6
Exp/Cntr=0.3,0.1

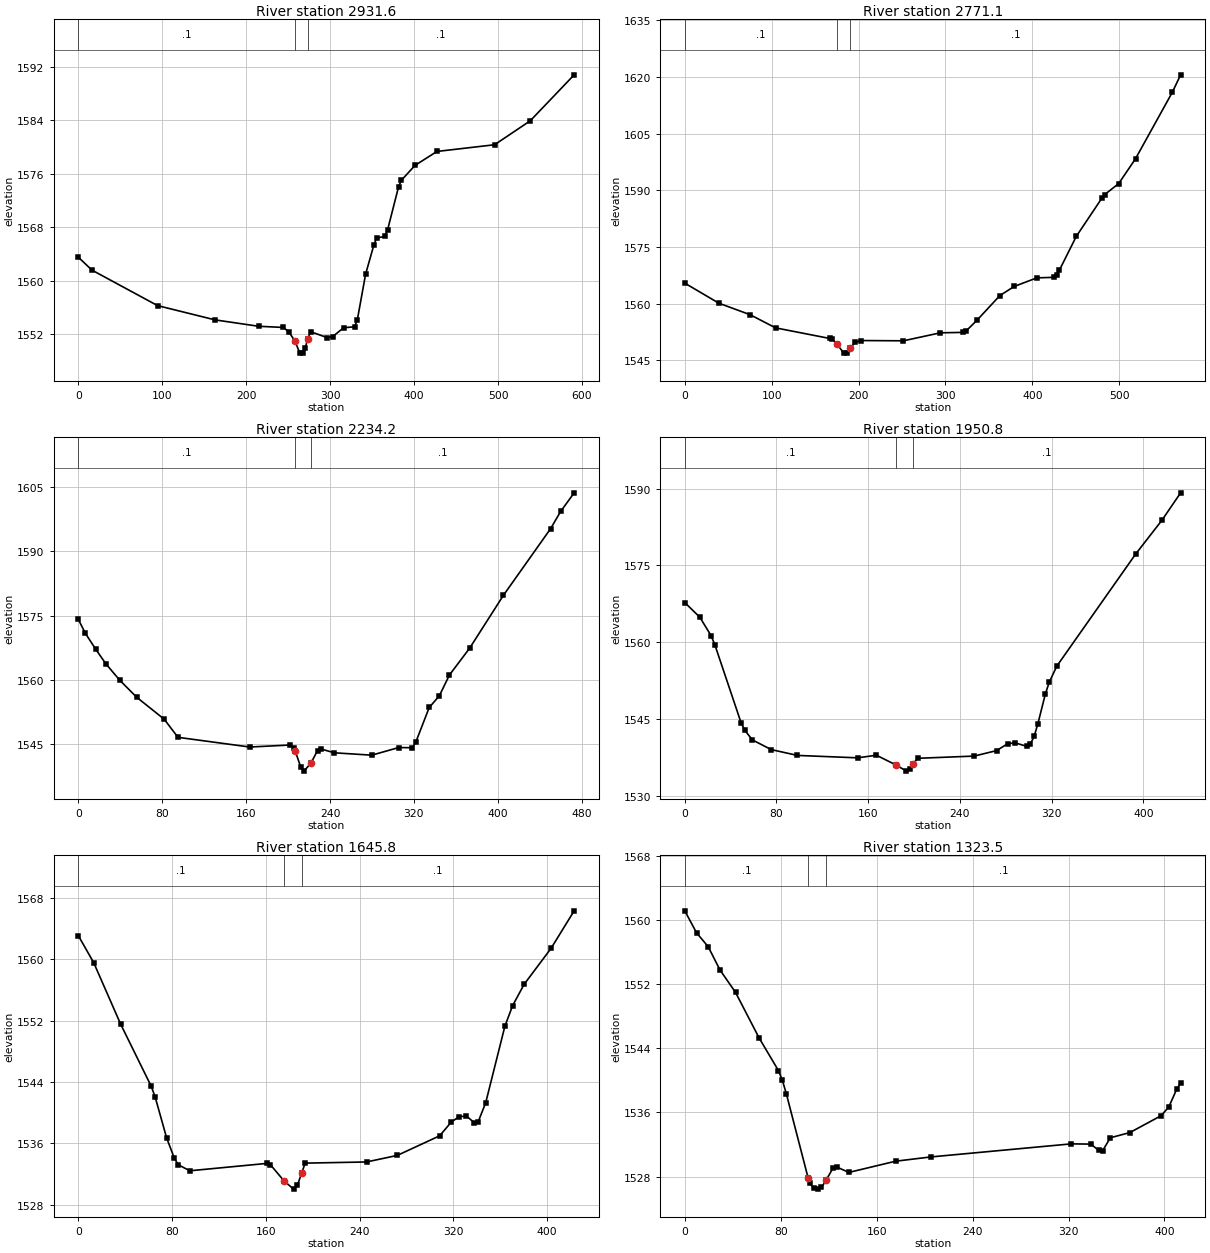
Type RM Length L Ch R = 1 ,2931.6,130.2,160.5,185.8
XS GIS Cut Line= 4
     2050402.471      252304.769     2050646.608      252298.211
     2050664.755      252242.351     2050946.053      252302.364
#Sta/Elev= 30
       0 1563.53    16.3 1561.60    94.4 1556.30   162.8 1554.17   214.9 1553.21
   244.2 1553.04   250.8 1552.36     258 1551.02   263.8 1549.20   267.1 1549.22
   270.3 1549.95     273 1551.30   276.9 1552.39   296.4 1551.52   303.0 1551.68
   316.0 1552.99   329.1 1553.14   332.4 1554.22   342.2 1561.01   352.0 1565.35
   355.3 1566.40   365.1 1566.65   368.3 1567.59   381.4 1574.04   384.7 1575.02
   401.0 1577.25   427.2 1579.34   495.8 1580.34   538.3 1583.92   590.6 1590.79
#Mann= 3 , 0 , 0
       0     0.1       0     258   0.045       0     273     0.1       0
Bank Sta=258,273
Exp/Cntr=0.3,0.1

Type RM Length L Ch R = 1 ,2771.1,545,536.8,525.9
XS GIS Cut Line= 3
     2050399.803      252149.255     2050827.320      252168.786
     2050952.564      252100.541
#Sta/Elev= 30
       0 1565.42    39.2 1560.12    75.1 1557.08   104.5 1553.59   166.6 1550.80
   169.9 1550.59   175.3 1549.24   183.0 1546.91   186.2 1546.99   190.3 1548.17
   196.0 1549.76   202.6 1550.24   251.6 1550.17   294.0 1552.28   320.2 1552.40
   323.4 1552.70   336.5 1555.67   362.6 1562.14   379.0 1564.54   405.1 1566.82
   424.7 1566.96   428.0 1567.63   431.2 1568.91   450.6 1577.82   479.8 1587.84
   483.1 1588.84   499.3 1591.75   518.7 1598.34   560.9 1615.86   570.6 1620.53
#Mann= 3 , 0 , 0
       0     0.1       0   175.3   0.045       0   190.3     0.1       0
Bank Sta=175.3,190.3
Exp/Cntr=0.3,0.1

Type RM Length L Ch R = 1 ,2234.2,272.3,283.4,292.5
XS GIS Cut Line= 4
     2050426.956      251785.003     2050567.581      251793.683
     2050732.512      251727.711     2050883.553      251758.961
#Sta/Elev= 30
       0 1574.12     6.6 1570.91    16.4 1567.22    26.2 1563.78    39.3 1559.98
    55.7 1555.95    81.9 1550.84    95.0 1546.62   163.5 1544.36   202.3 1544.83
   205.5 1544.16   206.8 1543.43   212.0 1539.75   215.2 1538.74   221.8 1540.61
   228.1 1543.54   231.3 1543.90   244.2 1543.01   279.8 1542.46   305.6 1544.24
   318.5 1544.19   321.7 1545.44   334.6 1553.58   344.2 1556.28   353.9 1561.16
   373.2 1567.42   405.3 1579.71   450.3 1595.25   459.9 1599.27   472.8 1603.62
#Mann= 3 , 0 , 0
       0     0.1       0   206.8   0.045       0   221.8     0.1       0
Bank Sta=206.8,221.8
Exp/Cntr=0.3,0.1

Type RM Length L Ch R = 1 ,1950.8,305.9,305,303.5
XS GIS Cut Line= 2
     2050458.397      251475.644     2050890.254      251501.685
#Sta/Elev= 30
       0 1567.75    13.1 1564.89    22.9 1561.29    26.2 1559.51    49.2 1544.18
    52.4 1542.75    59.0 1540.89    75.4 1539.00    98.3 1537.86   150.8 1537.39
   167.2 1537.90   184.1 1536.01   193.4 1534.79   196.7 1535.28   199.1 1536.19
   203.2 1537.30   252.4 1537.73   272.0 1538.80   281.9 1540.18   288.4 1540.30
   298.3 1539.65   301.5 1540.10   304.8 1541.58   308.1 1544.08   314.6 1549.90
   317.9 1552.13   324.5 1555.30   393.3 1577.22   416.2 1583.82   432.6 1589.21
#Mann= 3 , 0 , 0
       0     0.1       0   184.1   0.045       0   199.1     0.1       0
Bank Sta=184.1,199.1
Exp/Cntr=0.3,0.1

Type RM Length L Ch R = 1 ,1645.8,329.4,322.4,311.6
XS GIS Cut Line= 2
     2050473.154      251183.977     2050896.331      251186.147
#Sta/Elev= 30
       0 1563.09    13.1 1559.58    36.1 1551.56    62.3 1543.43    65.6 1542.04
    75.4 1536.71    82.0 1534.06    85.3 1533.23    95.1 1532.44   160.7 1533.40
   164.0 1533.22   175.5 1531.14   183.7 1530.05   187.0 1530.55   190.5 1532.10
   193.6 1533.44   246.0 1533.59   272.3 1534.45   308.4 1537.00   318.2 1538.77
   324.8 1539.48   331.3 1539.58   337.9 1538.71   341.2 1538.80   347.7 1541.31
   364.1 1551.30   370.7 1553.98   380.5 1556.75   403.5 1561.44   423.2 1566.33
#Mann= 3 , 0 , 0
       0     0.1       0   175.5   0.045       0   190.5     0.1       0
Bank Sta=175.5,190.5
Exp/Cntr=0.3,0.1

Type RM Length L Ch R = 1 ,1323.5,428.8,436.7,442
XS GIS Cut Line= 2
     2050462.737      250940.487     2050836.001      250762.536
#Sta/Elev= 30
       0 1561.12     9.8 1558.38    19.5 1556.65    29.3 1553.76    42.3 1550.96
    61.9 1545.30    78.1 1541.21    81.4 1539.99    84.7 1538.31   102.8 1527.86
   104.2 1527.19   107.4 1526.56   110.7 1526.44   114.0 1526.65   117.8 1527.54
   123.7 1529.09   127.0 1529.18   136.8 1528.52   175.8 1529.92   205.1 1530.45
   322.3 1532.08   338.6 1532.05   345.1 1531.28   348.4 1531.22   354.9 1532.84
   371.2 1533.49   397.2 1535.59   403.7 1536.69   410.3 1538.92   413.5 1539.66
#Mann= 3 , 0 , 0
       0     0.1       0   102.8   0.045       0   117.8     0.1       0
Bank Sta=102.8,117.8
Exp/Cntr=0.3,0.1

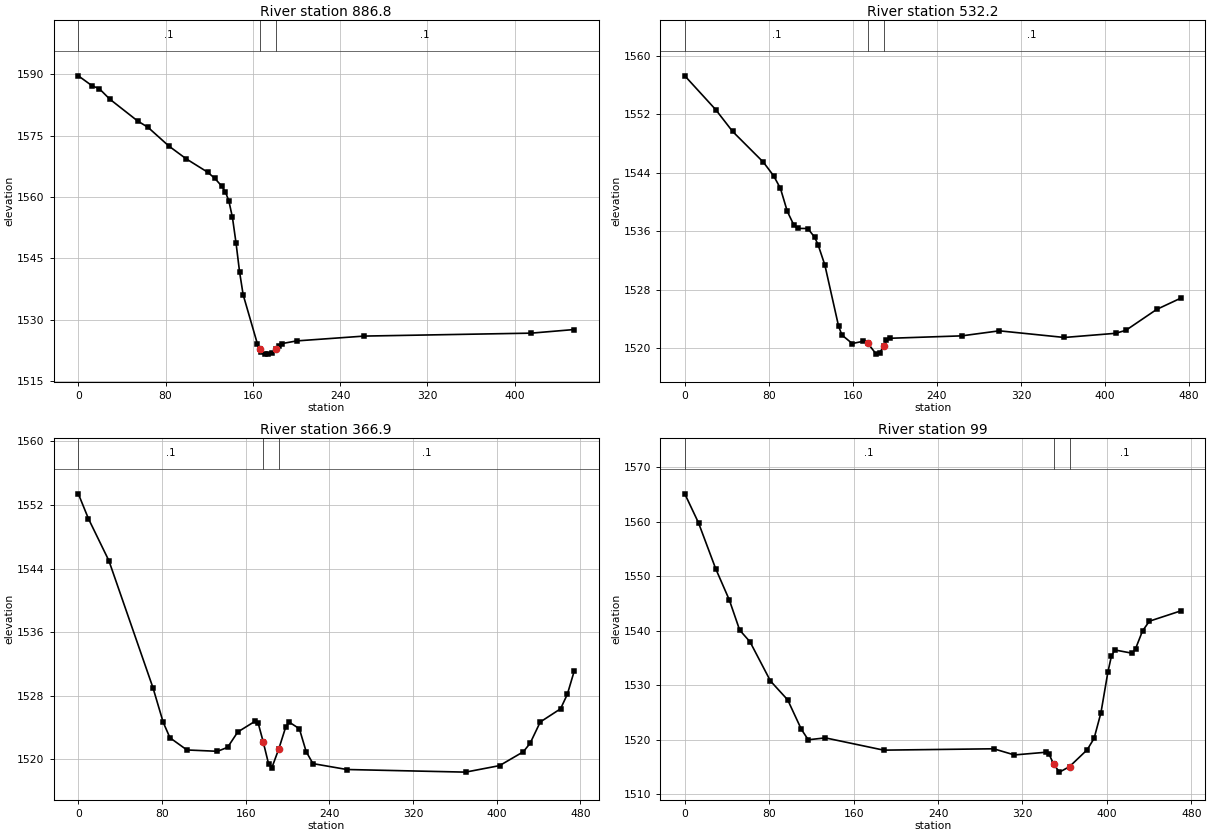
Type RM Length L Ch R = 1 ,886.8,352,354.6,354.8
XS GIS Cut Line= 3
     2050304.676      250595.173     2050348.664      250499.376
     2050693.640      250445.262
#Sta/Elev= 30
       0 1589.61    12.8 1587.14    19.2 1586.47    28.8 1583.92    54.3 1578.59
    63.9 1577.02    83.0 1572.45    99.0 1569.31   118.5 1566.07   125.0 1564.59
   131.5 1562.65   134.8 1561.26   138.0 1559.04   141.3 1555.00   144.6 1548.74
   147.8 1541.76   151.1 1536.13   164.2 1524.09   166.5 1522.74   167.4 1522.21
   170.7 1521.70   174.0 1521.60   177.2 1521.77   181.5 1522.90   183.7 1523.67
   187.0 1524.19   200.1 1524.83   262.1 1526.01   415.4 1526.73   454.6 1527.61
#Mann= 3 , 0 , 0
       0     0.1       0   166.5   0.045       0   181.5     0.1       0
Bank Sta=166.5,181.5
Exp/Cntr=0.3,0.1

Type RM Length L Ch R = 1 ,532.2,138.6,165.3,189
XS GIS Cut Line= 3
     2050239.572      250252.725     2050304.597      250159.322
     2050661.522      250129.723
#Sta/Elev= 30
       0 1557.26    29.3 1552.65    45.5 1549.65    74.8 1545.44    84.5 1543.59
    91.0 1541.87    97.6 1538.70   104.0 1536.78   107.3 1536.38   117.1 1536.36
   123.6 1535.17   126.8 1534.17   133.3 1531.38   146.4 1522.99   149.6 1521.78
   159.4 1520.62   169.2 1520.91   174.3 1520.64   182.2 1519.17   185.4 1519.27
   189.3 1520.33   192.0 1521.04   195.2 1521.34   263.6 1521.67   299.4 1522.36
   361.3 1521.45   410.1 1522.02   419.9 1522.43   449.2 1525.29   472.0 1526.82
#Mann= 3 , 0 , 0
       0     0.1       0   174.3   0.045       0   189.3     0.1       0
Bank Sta=174.3,189.3
Exp/Cntr=0.3,0.1

Type RM Length L Ch R = 1 ,366.9,281.7,267.9,254.2
XS GIS Cut Line= 4
     2050202.998      249955.141     2050359.248      249998.544
     2050385.289      250040.211     2050645.706      250005.489
#Sta/Elev= 30
       0 1553.40     9.7 1550.26    29.2 1544.99    71.4 1528.98    81.1 1524.66
    87.6 1522.70   103.8 1521.17   133.0 1521.00   142.7 1521.50   152.4 1523.43
   168.7 1524.76   172.0 1524.51   176.7 1522.21   181.8 1519.45   185.1 1518.96
   191.7 1521.33   198.2 1524.03   201.5 1524.68   211.3 1523.84   217.8 1520.96
   224.3 1519.45   256.7 1518.71   370.2 1518.38   402.7  1519.2   425.4 1520.94
   431.9 1522.01   441.6 1524.69   461.0 1526.35   467.5 1528.18   474.0 1531.07
#Mann= 3 , 0 , 0
       0     0.1       0   176.7   0.045       0   191.7     0.1       0
Bank Sta=176.7,191.7
Exp/Cntr=0.3,0.1

Type RM Length L Ch R = 1 ,99,104.6,99,93.3
XS GIS Cut Line= 3
     2050211.886      249788.661     2050478.202      249798.572
     2050665.642      249877.436
#Sta/Elev= 30
       0 1565.09    13.0 1559.77    29.2 1551.40    42.2 1545.63    52.0 1540.11
    61.8 1537.96    81.2 1530.77    97.5 1527.32   110.5 1521.90   117.0 1520.00
   133.2 1520.35   188.5 1518.10   292.7 1518.35   312.4 1517.22   341.9 1517.71
   345.2 1517.36   349.6 1515.52   355.1 1514.07   364.6 1515.08   381.3 1518.16
   387.9 1520.26   394.4 1524.97   401.0 1532.45   404.3 1535.32   407.5 1536.47
   423.9 1535.87   427.2 1536.70   433.8 1539.96   440.3 1541.74   469.9 1543.62
#Mann= 3 , 0 , 0
       0     0.1       0   349.6   0.045       0   364.6     0.1       0
Bank Sta=349.6,364.6
Exp/Cntr=0.3,0.1